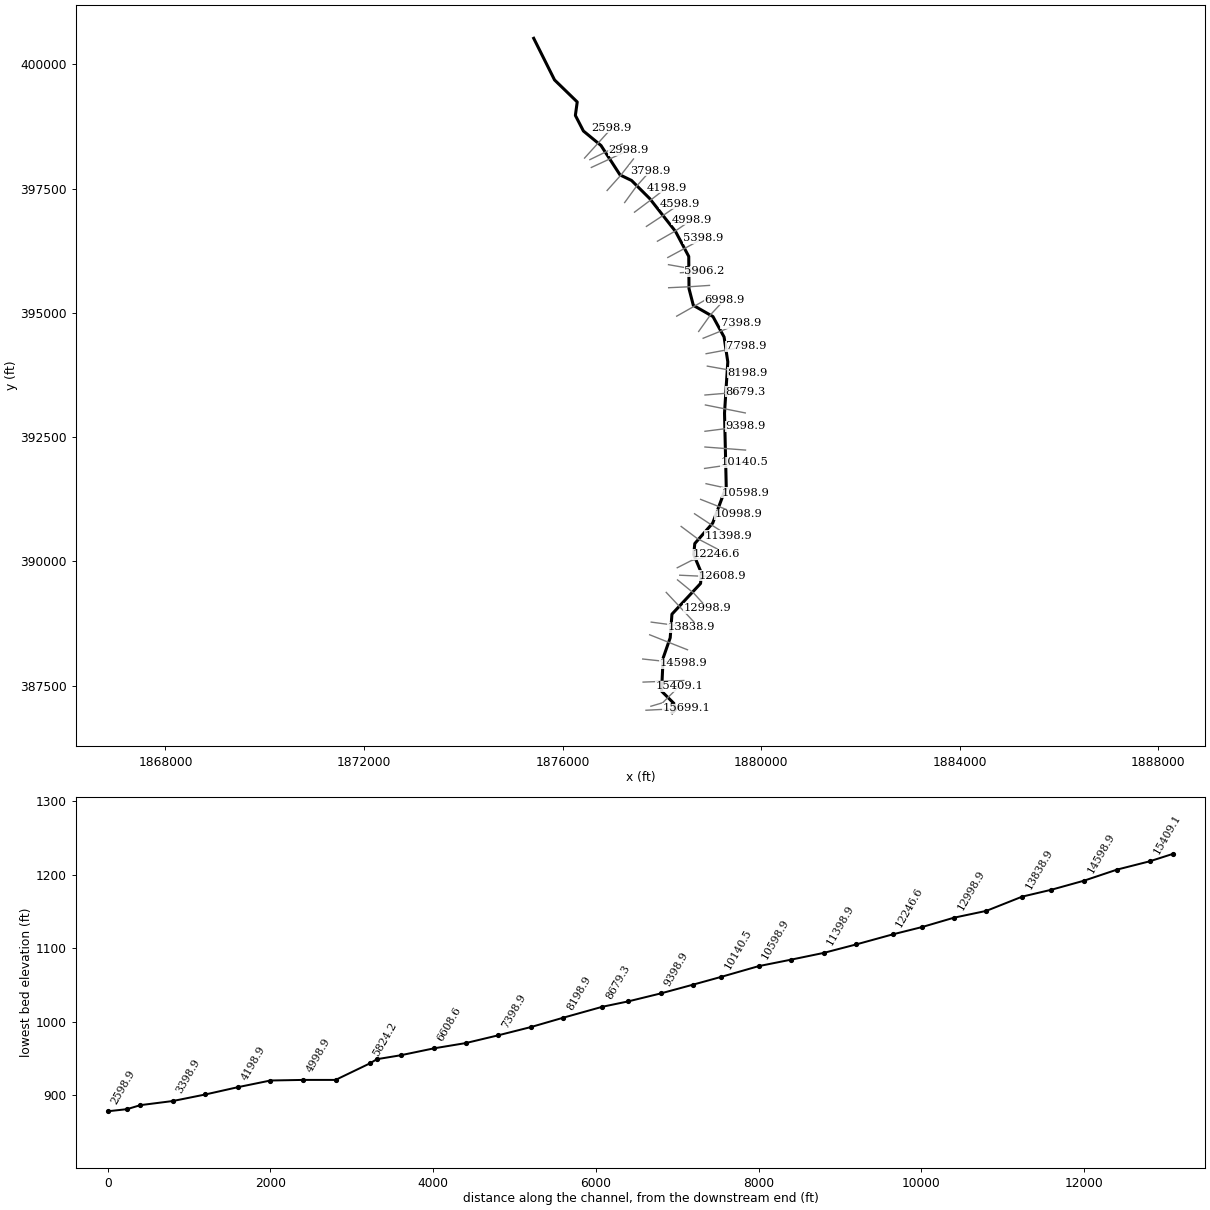
--- PowlltnFrk.prj (project) ---

Proj Title=PowlltnFrk
Current Plan=p01
Default Exp/Contr=0,0
English Units
Geom File=g01
Flow File=f01
Plan File=p01
BEGIN DESCRIPTION:
END DESCRIPTION:
DSS Export Rating Curves= 0
DSS Export Rating Curve Sorted= 0
DSS Export Volume Flow Curves= 0
DXF OffsetX= 0
DXF OffsetY= 0
DXF ScaleX= 0
DXF ScaleY= 0

--- PowlltnFrk.p01 (plan) ---

Plan Title=Floodplain
Program Version=4.00
Geom File=g01
Flow File=f01
K Sum by GR=0
Std Step Tol=0.01
Critical Tol=0.01
Num of Std Step Trials=20
Max Error Tol=0.3
Flow Tol Ratio=0.001
Split Flow NTrial=30
Split Flow Tol=0.02
Split Flow Ratio=0.02
Log Output Level=0
Friction Slope Method=1
Unsteady Friction Slope Method=2
Unsteady Bridges Friction Slope Method=1
Global Log Level=0
CheckData=False
Run HTab=0
Run UNet=0
Run PostProcess=0
UNET Theta=0
UNET Theta Warmup=0
UNET ZTol=0
UNET ZSATol=0
UNET MxIter=0
UNET MaxInSteps=0
UNET DtIC=0
UNET DtMin=0
UNET MaxCRTS=0
UNET WFStab=0
UNET SFStab=0
UNET WFX=0
UNET SFX=0
UNET DSS MLevel=0
UNET DZMax Abort=0
UNET Convert EG Bridges=0
UNET Use Existing IB Tables=0
UNET Froude Limit=0
UNET Froude Power=0
Write IC File=0
Echo Input=False
Echo Output=False
Write Detailed=0

--- PowlltnFrk.f01 (steady flow) ---

Flow Title=NFF Regression Equation
Program Version=4.00
Number of Profiles=1
Profile Names=P100yr
River Rch & RM=PowlltnFrk,Main      ,15699.1
927.2205
River Rch & RM=PowlltnFrk,Main      ,12608.9
1013.337
River Rch & RM=PowlltnFrk,Main      ,12246.6
1214.762
River Rch & RM=PowlltnFrk,Main      ,10140.5
1310.788
River Rch & RM=PowlltnFrk,Main      ,6608.6
1455.875
River Rch & RM=PowlltnFrk,Main      ,6198.9
1672.364
River Rch & RM=PowlltnFrk,Main      ,4598.9
1759.509
River Rch & RM=PowlltnFrk,Main      ,198.5
1923.737
Boundary for River Rch & Prof#=PowlltnFrk,Main      ,1
Up Type=0
Dn Type=3
Dn Slope=0.016016

--- PowlltnFrk.g01 (geometry) ---

Geom Title=USGS 3m DEM
Program Version=4.10

River Reach=PowlltnFrk      ,Main
Reach XY= 30
      1878206.62       386952.41     1878270.276      387011.998
     1878242.448      387137.993     1877992.663      387386.649
     1878024.329      388053.105      1878166.69      388461.091
     1878201.485      388935.536     1878777.801      389553.104
     1878795.162       389764.91     1878640.648       390134.09
     1878661.482      390356.924     1879022.593      390768.382
     1879295.162      391501.021      1879260.44       392983.66
     1879326.412      394013.174     1879251.759      394513.174
     1879027.801      394924.632     1878632.034      395150.721
     1878545.162      395487.132     1878539.954      396134.702
     1878274.329      396636.438     1877755.232      397297.896
     1877387.769      397663.546     1877156.273      397775.327
     1876772.593      398367.341     1876418.426      398659.007
     1876256.364      398972.866     1876293.622      399243.521
     1875836.829      399686.785     1875417.204      400524.679

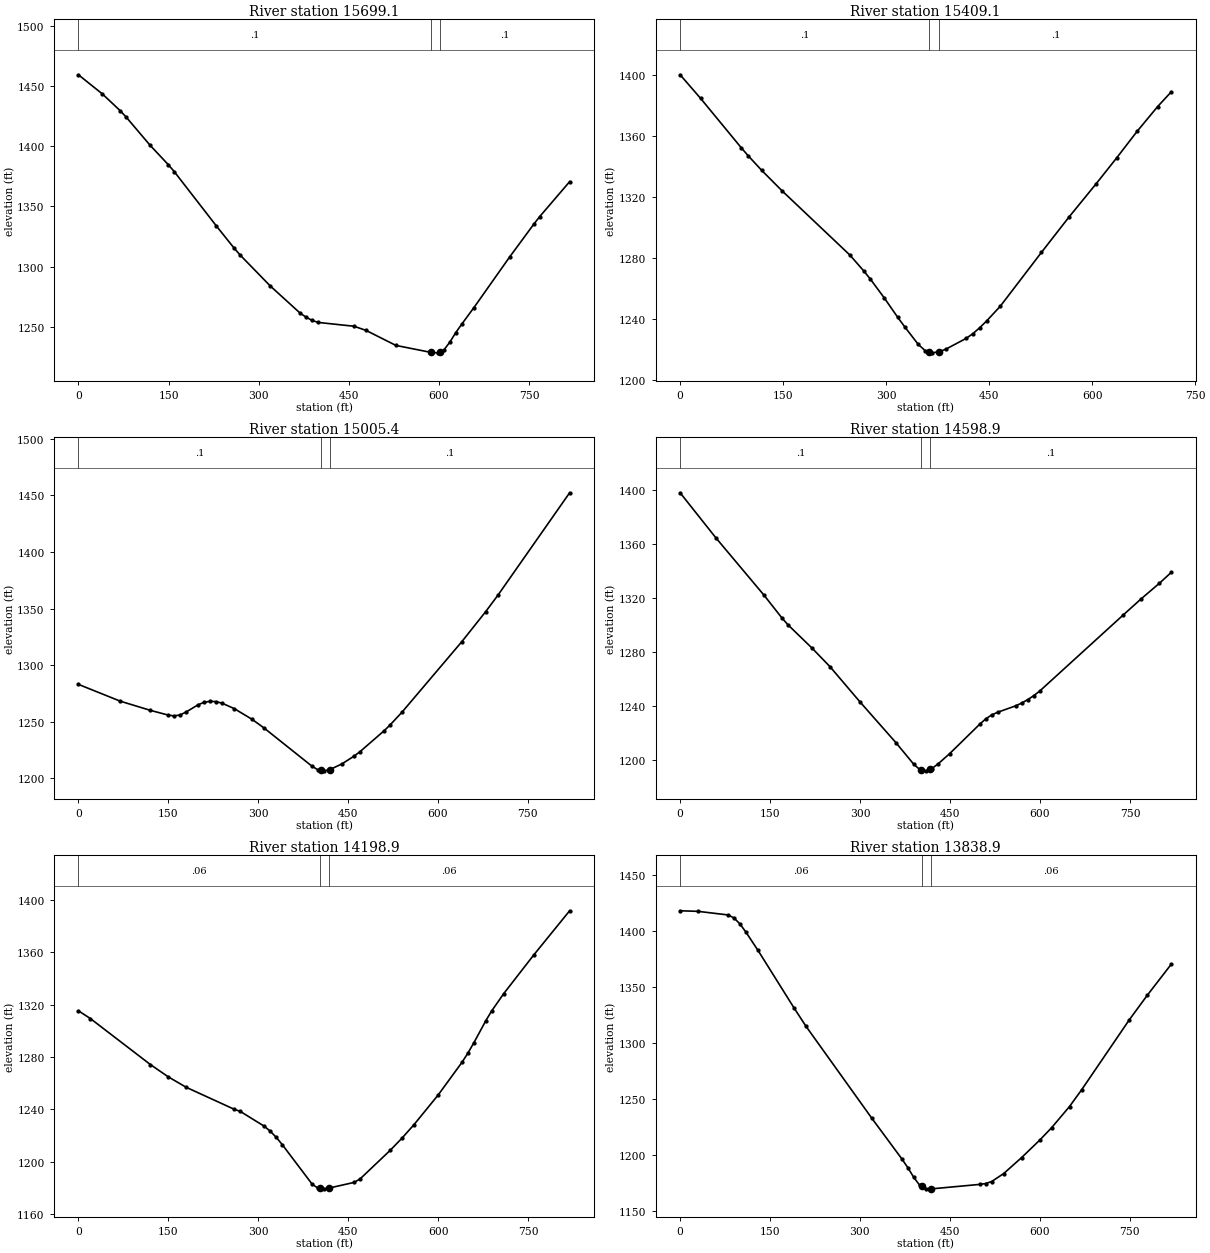
Type RM Length L Ch R = 1 ,15699.1 ,274.3,289.9,305.5
XS GIS Cut Line= 2
     1877678.294      387002.411     1878494.868       387043.24
#Sta/Elev= 30
       0 1459.37    39.9 1443.44    69.8  1429.4    79.8 1424.03   119.6 1400.62
   149.6 1384.68   159.5 1378.92   229.3 1333.95   259.2  1315.3   269.2 1309.58
   319.1    1284   368.9 1261.38   378.9 1257.97   388.9  1255.3   398.8 1253.61
   458.6 1250.43   478.6    1247   528.4 1234.51   587.3 1228.64   598.2 1228.33
   602.3 1229.28   608.2 1230.65   618.2 1237.22   628.2 1245.22   638.1 1252.21
   658.1 1265.79   717.9 1308.08   757.8 1335.14   767.7 1341.48   817.6 1370.55
#Mann= 3 , 0 , 0
       0      .1       0   587.3    .045       0   602.3      .1       0
Bank Sta=587.3,602.3
XS Rating Curve= 0 ,0
Exp/Cntr=0.3,0.1

Type RM Length L Ch R = 1 ,15409.1 ,419.5,403.5,387.5
XS GIS Cut Line= 3
     1877777.791      387082.598     1878014.671       387153.22
     1878347.186      387482.793
#Sta/Elev= 30
       0 1400.38    29.7 1384.96      89 1352.54    98.9 1347.39   118.6  1337.8
   148.3 1324.35   247.2 1282.17   267.1 1271.92   277.1 1266.36     297 1254.24
   316.9 1241.34   326.9  1235.2   346.8 1223.58   356.8 1219.52   362.5 1218.67
   366.7 1218.04   377.5 1218.78   386.6 1220.35   416.5  1227.5   426.5 1230.65
   436.4 1234.56   446.4 1238.96   466.3 1248.62   526.1 1283.84   565.9 1306.85
   605.8 1328.87   635.7 1345.84   665.6 1363.32   695.4  1379.5   715.4 1389.25
#Mann= 3 , 0 , 0
       0      .1       0   362.5    .045       0   377.5      .1       0
Bank Sta=362.5,377.5
XS Rating Curve= 0 ,0
Exp/Cntr=0.3,0.1

Type RM Length L Ch R = 1 ,15005.4 ,409.7,406.4,403.4
XS GIS Cut Line= 2
     1877620.575      387568.494     1878440.146      387600.956
#Sta/Elev= 30
       0 1283.06      70  1268.2     120 1260.14     150 1255.93     160  1255.2
     170 1256.11     180 1258.72     200  1265.1     210 1267.21   220.1 1268.14
   230.1  1267.8   240.1 1266.39   260.1 1261.68   290.1 1252.15   310.1 1244.48
   390.1 1210.75   400.1 1207.57   404.7 1207.17   410.1  1206.7   419.7 1207.76
   440.1 1212.87   460.1 1219.62   470.1 1223.59   510.1 1241.95   520.1 1247.05
   540.1 1258.38   640.2 1320.79   680.2 1347.41   700.2 1361.62   820.2 1452.27
#Mann= 3 , 0 , 0
       0      .1       0   404.7    .045       0   419.7      .1       0
Bank Sta=404.7,419.7
XS Rating Curve= 0 ,0
Exp/Cntr=0.3,0.1

Type RM Length L Ch R = 1 ,14598.9 ,406.1,399.9,393.5
XS GIS Cut Line= 3
     1877612.732      388033.349     1878019.894      387989.724
     1878427.645      387951.451
#Sta/Elev= 30
       0 1398.18    59.9 1364.55   139.8 1322.14   169.8 1305.14   179.8 1300.11
   219.7 1282.89   249.7 1269.08   299.6 1242.96   359.6 1212.64   389.5 1196.52
   399.5  1192.6     402 1192.35   409.5 1191.61     417 1192.85   419.5 1193.26
   429.5 1196.55   449.4 1204.39   499.4  1226.2   509.4 1230.16   519.4 1233.13
   529.4 1235.12   559.3 1239.87   569.3 1241.92   579.3 1244.44   589.3 1247.37
   599.3 1250.79   739.1 1307.53   769.1 1319.56   799.1 1330.95     819  1339.1
#Mann= 3 , 0 , 0
       0      .1       0     402    .045       0     417      .1       0
Bank Sta=402,417
XS Rating Curve= 0 ,0
Exp/Cntr=0.3,0.1

Type RM Length L Ch R = 1 ,14198.9 ,354.3,359.9,365.4
XS GIS Cut Line= 3
     1877753.066      388521.051     1878133.996      388369.286
     1878514.908      388219.229
#Sta/Elev= 30
       0 1315.25      20  1309.3     120 1274.22     150 1264.78     180 1256.79
     260 1240.04     270 1238.44     310 1227.12     320 1223.33     330 1218.62
     340  1213.1     390 1182.82     400 1179.74   402.6 1179.63     410 1179.32
   417.6 1179.87     460 1184.24     470 1186.95   519.9 1208.63   539.9  1218.1
   559.8 1228.33   599.8  1250.8   639.7 1275.81   649.7 1282.93   659.7 1290.88
   679.7 1307.77   689.6  1315.3   709.6 1328.44   759.5 1357.84   819.4 1391.59
#Mann= 3 , 0 , 0
       0     .06       0   402.6    .045       0   417.6     .06       0
Bank Sta=402.6,417.6
XS Rating Curve= 0 ,0
Exp/Cntr=0.3,0.1

Type RM Length L Ch R = 1 ,13838.9 ,455.3,439.7,424.1
XS GIS Cut Line= 2
     1877784.034      388775.873     1878596.553      388667.956
#Sta/Elev= 30
       0  1417.7      30 1417.19      80 1413.98      90 1411.27     100 1405.84
     110 1398.52     130 1382.34   189.9 1331.27   209.9 1314.86   319.9 1232.78
   369.8 1196.72   379.8  1188.9   389.8 1180.19   399.8 1173.05   402.8 1172.14
   409.8 1170.02   417.8 1169.95   419.8 1169.93   499.8 1173.88   509.8 1174.65
   519.8 1176.44   539.8 1183.52   569.8  1197.8   599.8 1213.24   619.7 1224.33
   649.7 1243.29   669.7 1258.03   749.7 1320.74   779.7  1342.6   819.6 1370.17
#Mann= 3 , 0 , 0
       0     .06       0   402.8    .045       0   417.8     .06       0
Bank Sta=402.8,417.8
XS Rating Curve= 0 ,0
Exp/Cntr=0.3,0.1

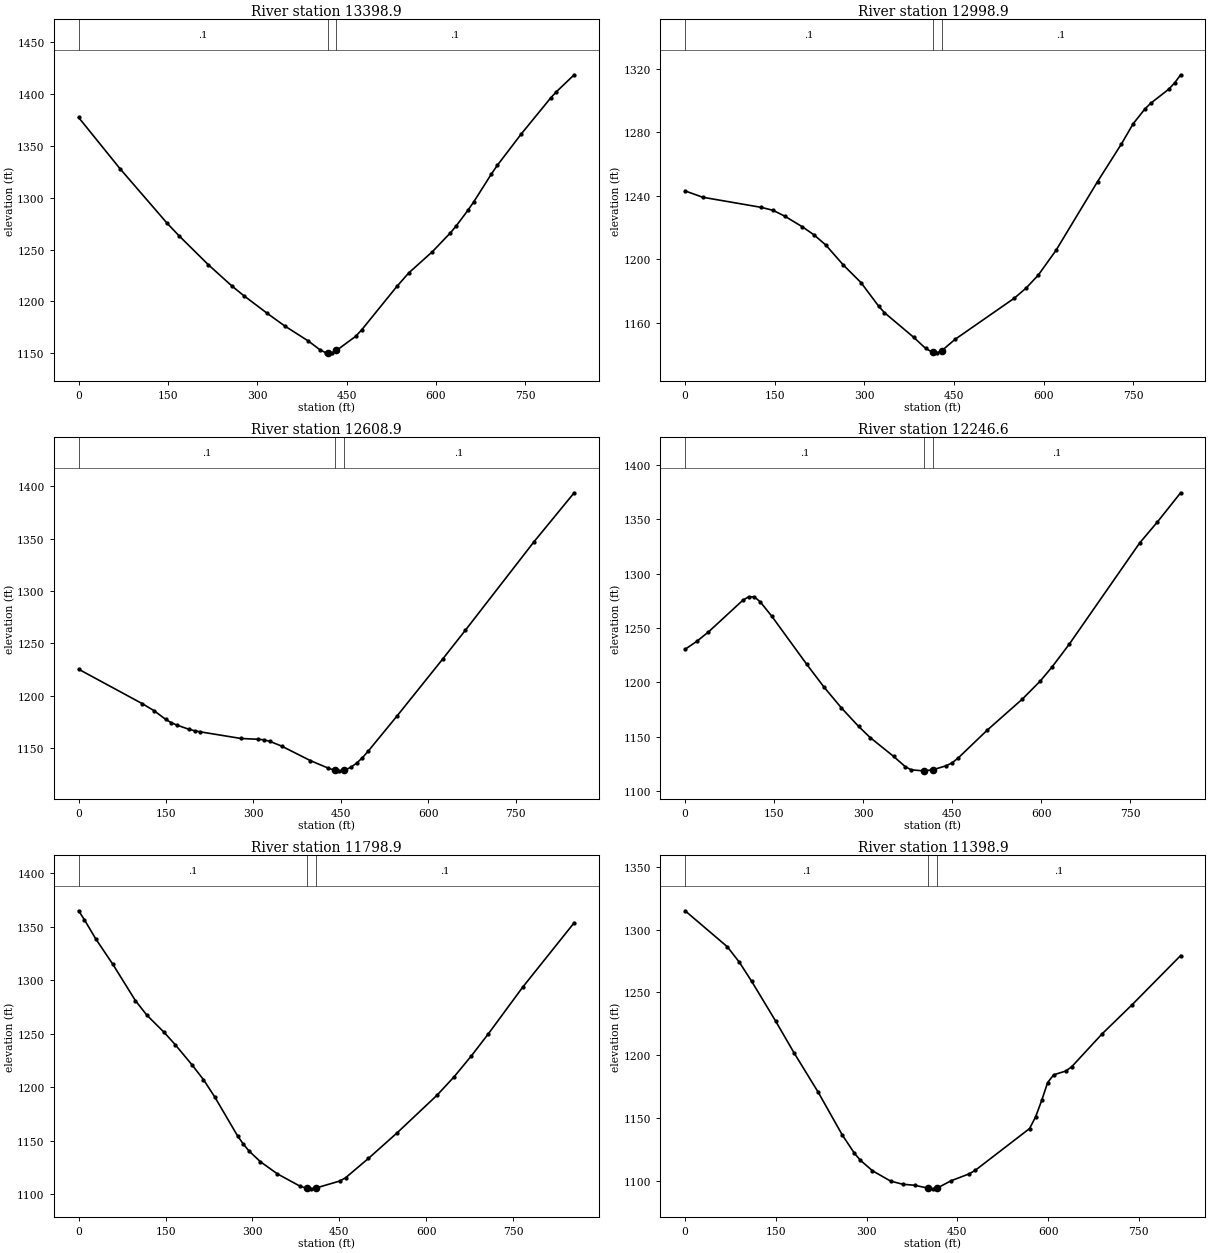
Type RM Length L Ch R = 1 ,13398.9 ,396.9,400,399.7
XS GIS Cut Line= 3
      1878086.52      389374.011     1878377.444      389063.458
     1878655.507      388766.573
#Sta/Elev= 30
       0 1377.13    69.3 1327.97   148.4 1275.48   168.2  1263.5   217.7 1235.49
   257.3 1214.98   277.1 1205.76   316.7 1188.63   346.4 1176.36     386 1161.89
   405.7 1153.35   415.6 1150.58     418 1150.59   425.5 1150.62     433 1152.85
   465.2 1166.42   475.1 1172.47   534.7 1214.63   554.5 1227.51   594.2 1247.97
     624 1265.79   633.9 1272.55   653.7 1287.68   663.6 1295.87   693.4 1322.83
   703.3 1331.13     743 1360.94   792.6 1395.75   802.5 1401.92   832.3 1418.22
#Mann= 3 , 0 , 0
       0      .1       0     418    .045       0     433      .1       0
Bank Sta=418,433
XS Rating Curve= 0 ,0
Exp/Cntr=0.3,0.1

Type RM Length L Ch R = 1 ,12998.9 ,375.6,390.1,409.5
XS GIS Cut Line= 3
     1878313.954      389625.546     1878640.318      389358.002
     1878914.733      389057.031
#Sta/Elev= 30
       0 1243.13    29.4 1239.14   127.6 1232.76   147.2  1230.9   166.8 1227.24
   196.3 1220.53   215.9 1215.42   235.5 1209.06     265 1196.43   294.4 1185.44
   323.9 1170.62   333.7  1166.5   382.8 1150.95   402.4 1144.09   414.5 1141.49
     422 1141.25   429.5 1142.61   451.8 1149.74   551.2  1175.7     571 1182.11
   590.9 1190.08   620.7 1205.72   690.2 1248.96     730 1272.54   749.8 1285.35
   769.7 1294.78   779.6 1298.37   809.4 1307.11   819.4 1311.14   829.3 1316.18
#Mann= 3 , 0 , 0
       0      .1       0   414.5    .045       0   429.5      .1       0
Bank Sta=414.5,429.5
XS Rating Curve= 0 ,0
Exp/Cntr=0.3,0.1

Type RM Length L Ch R = 1 ,12608.9 ,355.8,362.2,366.8
XS GIS Cut Line= 3
       1878358.5      389719.789     1878805.514      389698.938
     1879207.948      389712.112
#Sta/Elev= 30
       0 1225.47   109.4 1192.58   129.3 1185.96   149.2 1177.73   159.1 1174.46
   169.1  1172.1   188.9 1168.28   198.9 1166.79   208.8 1165.77   278.4 1159.45
   308.3 1158.67   318.2 1158.14   328.2 1156.67   348.1 1152.22   397.8 1138.28
   427.6 1131.34   437.6 1129.36   439.7  1129.2   447.5 1128.59   454.7  1129.2
   457.3 1129.42   467.1 1132.02     477 1135.95   486.8 1141.03   496.6 1147.21
   545.7 1180.48   624.3 1234.96   663.6 1262.68   781.4 1347.09   850.2 1393.69
#Mann= 3 , 0 , 0
       0      .1       0   439.7    .045       0   454.7      .1       0
Bank Sta=439.7,454.7
XS Rating Curve= 0 ,0
Exp/Cntr=0.3,0.1

Type RM Length L Ch R = 1 ,12246.6 ,467.5,447.6,431.3
XS GIS Cut Line= 3
     1878308.698      389870.005     1878586.457      390011.598
     1879093.805      390139.134
#Sta/Elev= 30
       0 1230.36    19.5 1237.59      39 1246.12    97.4 1275.53   107.2 1278.67
   116.9 1278.56   126.7 1273.92   146.1 1260.76   204.6  1216.8   233.8 1195.76
     263 1176.67   292.3 1159.46   311.8 1149.18   351.2  1131.9     371  1122.4
   380.9 1119.51   400.6 1118.57   402.1 1118.61   417.1 1119.47   440.1 1123.29
     450    1126   459.8 1130.22   509.2 1156.08   568.4 1184.66     598 1200.94
   617.8 1213.77   647.4 1235.18   765.8 1328.11   795.4 1347.22   834.9 1374.31
#Mann= 3 , 0 , 0
       0      .1       0   402.1    .045       0   417.1      .1       0
Bank Sta=402.1,417.1
XS Rating Curve= 0 ,0
Exp/Cntr=0.3,0.1

Type RM Length L Ch R = 1 ,11798.9 ,398.6,400,398
XS GIS Cut Line= 3
     1878387.148      390701.114     1878708.487      390460.108
     1879110.748      390249.969
#Sta/Elev= 30
       0  1364.7     9.8 1356.49    29.4 1338.58    58.8 1314.93      98 1280.81
   117.6 1267.31     147 1251.47   166.6 1239.75   195.9 1220.67   215.5 1206.98
   235.1 1190.68   274.3 1154.49   284.1 1146.93   293.9 1140.45   313.5 1130.41
   342.9 1119.01   382.1 1107.47   394.2 1105.29   401.7 1104.94   409.2 1105.61
     451 1112.28   460.9  1115.3   500.3 1133.35   549.7 1157.18   618.7 1192.38
   648.3 1209.66   677.9 1229.06   707.5 1249.87   766.7 1293.39   855.5  1353.5
#Mann= 3 , 0 , 0
       0      .1       0   394.2    .045       0   409.2      .1       0
Bank Sta=394.2,409.2
XS Rating Curve= 0 ,0
Exp/Cntr=0.3,0.1

Type RM Length L Ch R = 1 ,11398.9 ,395.3,400,404.3
XS GIS Cut Line= 3
     1878656.948      390956.461     1878998.827      390730.906
     1879344.641      390511.609
#Sta/Elev= 30
       0 1315.06    69.9 1286.34    89.9  1273.9   109.9 1258.92   149.8 1227.02
   179.8 1202.04   219.8 1170.58   259.7 1136.42   279.7  1121.9   289.7 1116.19
   309.7 1107.82   339.6 1099.58   359.6 1097.06   379.6 1096.23   402.1 1093.88
   409.6 1093.39   417.1  1094.1   439.5  1099.8   469.5 1105.31   479.5 1108.11
   569.4 1141.45   579.4 1150.81   589.4 1163.84   599.3 1178.14   609.3  1184.3
   629.3 1187.32   639.3 1190.85   689.2 1216.89   739.2 1240.32   819.1 1279.37
#Mann= 3 , 0 , 0
       0      .1       0   402.1    .045       0   417.1      .1       0
Bank Sta=402.1,417.1
XS Rating Curve= 0 ,0
Exp/Cntr=0.3,0.1

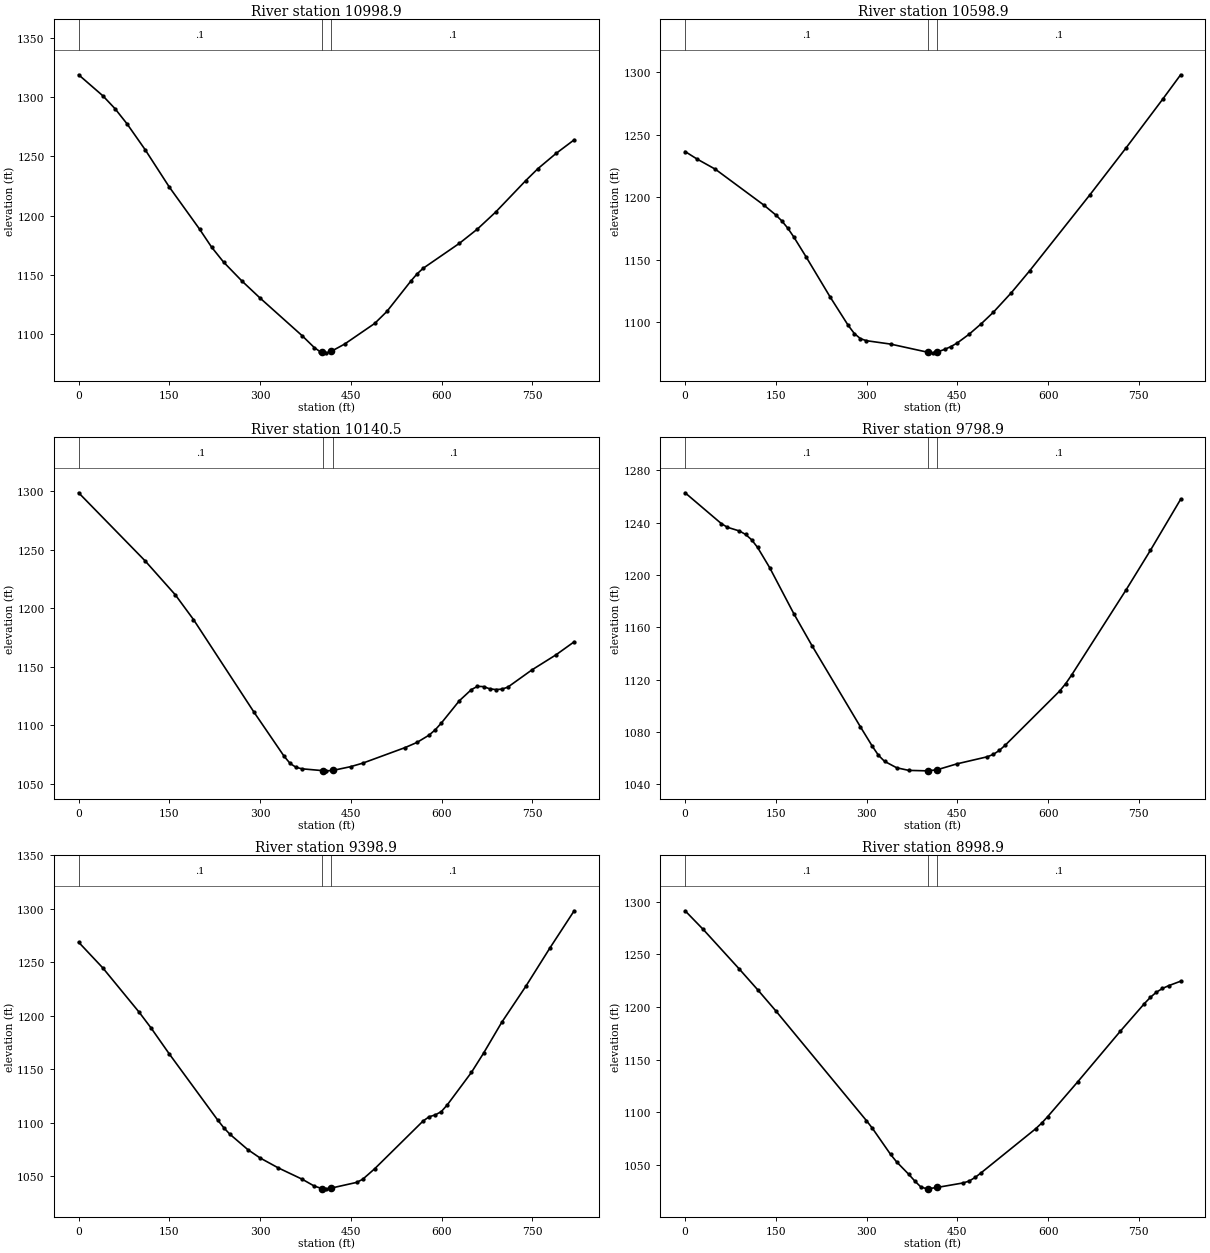
Type RM Length L Ch R = 1 ,10998.9 ,396.4,400,403.3
XS GIS Cut Line= 3
     1878778.766      391246.123     1879159.768      391096.031
     1879540.771      390945.939
#Sta/Elev= 30
       0  1318.7      40    1301    59.9 1290.26    79.9 1277.41   109.9 1255.57
   149.8 1224.08   199.8 1188.59   219.7 1173.41   239.7 1160.67   269.7  1144.9
   299.6 1130.56   369.6 1098.59   389.5 1088.68   399.5 1085.08     402 1084.87
   409.5 1084.24     417 1085.37   439.5  1091.6   489.4 1109.06   509.4  1119.1
   549.3  1144.9   559.3 1150.78   569.3 1155.49   629.2 1176.53   659.2 1188.66
   689.2 1202.91   739.1 1229.54   759.1 1239.56     789 1252.36     819 1263.85
#Mann= 3 , 0 , 0
       0      .1       0     402    .045       0     417      .1       0
Bank Sta=402,417
XS Rating Curve= 0 ,0
Exp/Cntr=0.3,0.1

Type RM Length L Ch R = 1 ,10598.9 ,450.2,458.4,467.1
XS GIS Cut Line= 3
     1878888.731      391561.353     1879288.851      391473.972
      1879687.63      391380.923
#Sta/Elev= 30
       0 1236.62      20 1230.55      50 1222.45   129.9 1193.83   149.8 1185.86
   159.8 1181.08   169.8 1175.17   179.8 1168.06   199.8 1152.39   239.7 1120.14
   269.7 1097.28   279.7 1090.86   289.7 1086.77   299.7 1085.11   339.6 1082.39
     402 1075.76   409.6 1075.38     417 1076.07   429.5 1078.24   439.5 1080.44
   449.5 1083.18   469.5 1090.32   489.4 1098.66   509.4 1107.86   539.4 1123.64
   569.4 1141.04   669.2 1202.07   729.2 1239.79   789.1 1278.39     819  1298.1
#Mann= 3 , 0 , 0
       0      .1       0     402    .045       0     417      .1       0
Bank Sta=402,417
XS Rating Curve= 0 ,0
Exp/Cntr=0.3,0.1

Type RM Length L Ch R = 1 ,10140.5 ,346.5,341.5,336.3
XS GIS Cut Line= 3
     1878858.624      391868.666     1879263.853      391927.608
     1879668.358      391991.618
#Sta/Elev= 30
       0 1298.71   109.9 1240.46   159.8 1211.41   189.8 1190.29   289.6 1111.21
   339.6 1073.31   349.6 1067.13   359.6 1063.77   369.5 1062.56   404.7 1060.95
   409.5 1060.84   419.7 1061.15   449.4 1064.39   469.4 1067.39   539.4  1080.7
   559.3 1085.17   579.3 1091.42   589.3 1095.92   599.3 1101.62   629.2 1120.79
   649.2 1130.36   659.2 1133.12   669.2 1132.89   679.2 1131.05   689.2 1130.38
   699.2  1130.7   709.2 1132.39   749.1 1147.16   789.1 1160.13     819 1171.22
#Mann= 3 , 0 , 0
       0      .1       0   404.7    .045       0   419.7      .1       0
Bank Sta=404.7,419.7
XS Rating Curve= 0 ,0
Exp/Cntr=0.3,0.1

Type RM Length L Ch R = 1 ,9798.9  ,395.4,399.9,404.5
XS GIS Cut Line= 3
     1878866.266       392299.81     1879274.604      392268.992
     1879682.943      392238.174
#Sta/Elev= 30
       0 1262.84    59.9 1239.29    69.9 1236.49    89.9 1233.63    99.9 1231.03
   109.9 1226.96   119.8 1221.07   139.8 1205.61   179.8 1170.36   209.7 1146.05
   289.6 1084.11   309.6 1069.05   319.6 1062.25   329.6 1057.66   349.6 1052.74
   369.6 1050.73   399.5 1050.38     402 1050.41     417 1051.26   449.4 1055.73
   499.4 1061.12   509.4 1062.94   519.4    1066   529.4  1070.1   619.2 1111.44
   629.2 1117.11   639.2 1123.84   729.1 1188.85   769.1  1218.9     819 1257.86
#Mann= 3 , 0 , 0
       0      .1       0     402    .045       0     417      .1       0
Bank Sta=402,417
XS Rating Curve= 0 ,0
Exp/Cntr=0.3,0.1

Type RM Length L Ch R = 1 ,9398.9  ,407.3,400,392.7
XS GIS Cut Line= 3
     1878866.905      392616.243     1879273.128      392667.945
     1879679.351      392719.646
#Sta/Elev= 30
       0 1268.94      40 1244.88    99.9 1203.58   119.8 1188.69   149.8 1164.52
   229.7 1102.79   239.7 1095.63   249.7 1089.57   279.7 1075.01   299.6 1067.34
   329.6 1058.06   369.6 1047.33   389.5 1040.94     402 1038.66   409.5 1038.37
     417 1039.01   459.4 1044.38   469.4 1047.26   489.4  1057.2   569.3 1101.78
   579.3 1105.74   589.3 1107.47   599.3 1110.51   609.3 1116.88   649.2 1147.24
   669.2 1165.16   699.2 1193.96   739.1 1227.73     779 1263.63     819 1298.32
#Mann= 3 , 0 , 0
       0      .1       0     402    .045       0     417      .1       0
Bank Sta=402,417
XS Rating Curve= 0 ,0
Exp/Cntr=0.3,0.1

Type RM Length L Ch R = 1 ,8998.9  ,313.3,319.7,326
XS GIS Cut Line= 3
     1878875.631      393145.929     1879277.179      393065.619
     1879678.727      392985.309
#Sta/Elev= 30
       0  1291.3      30 1273.58    89.9 1235.85   119.8 1216.49   149.8 1196.44
   299.6 1092.31   309.6 1084.94   339.6 1060.21   349.6  1053.1   369.6 1041.34
   379.5 1035.03   389.5 1029.39   399.5 1027.53     402 1027.68     417 1028.89
   459.4 1033.12   469.4 1034.88   479.4 1038.38   489.4  1042.8   579.3 1084.47
   589.3 1089.86   599.3 1096.05   649.2 1129.26   719.1 1176.92   759.1 1203.27
   769.1 1209.24     779  1214.1     789 1217.62     799  1220.2     819  1224.5
#Mann= 3 , 0 , 0
       0      .1       0     402    .045       0     417      .1       0
Bank Sta=402,417
XS Rating Curve= 0 ,0
Exp/Cntr=0.3,0.1

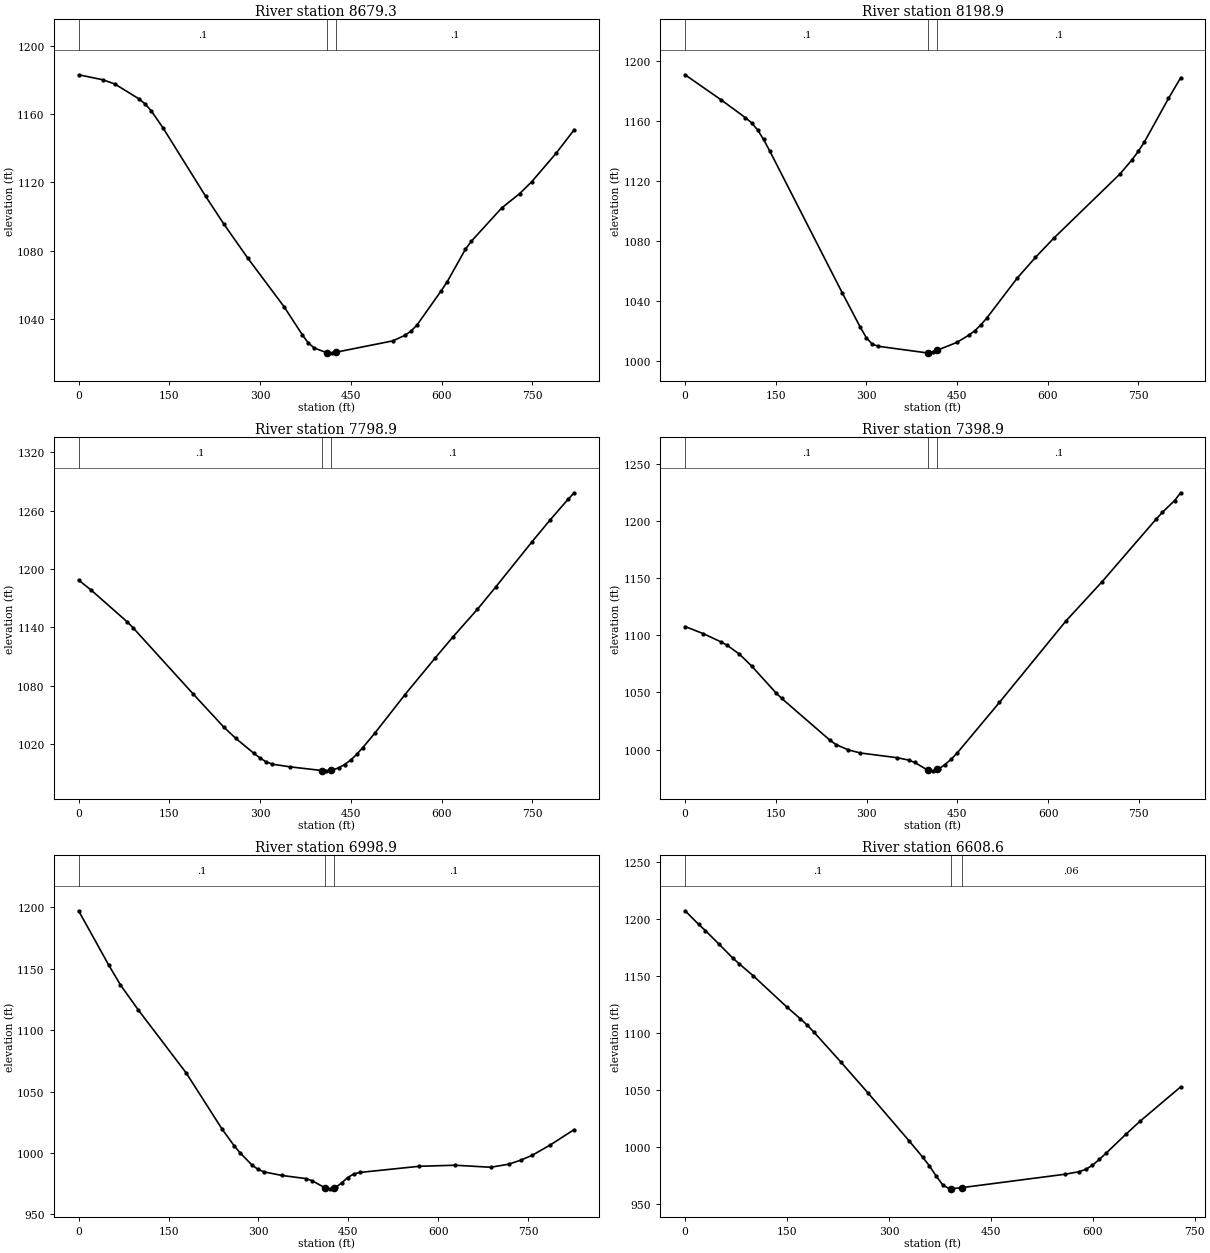
Type RM Length L Ch R = 1 ,8679.3  ,486.1,480.3,475
XS GIS Cut Line= 3
     1878866.856       393346.12     1879274.942      393380.127
     1879683.027      393414.135
#Sta/Elev= 30
       0 1182.91      40 1179.99    59.9  1177.5    99.9 1168.77   109.9 1165.82
   119.8 1161.92   139.8 1151.66   209.7  1111.9   239.7 1095.71   279.7 1075.53
   339.6 1047.13   369.6  1030.8   379.5 1025.99   389.5 1022.97   410.2 1020.24
   419.5 1020.17   425.2 1020.53   519.4 1027.18   539.3 1030.43   549.3 1032.88
   559.3 1036.47   599.3 1056.53   609.3 1061.87   639.2 1080.77   649.2 1085.54
   699.2 1104.96   729.1 1113.41   749.1 1120.42     789 1136.92     819 1150.72
#Mann= 3 , 0 , 0
       0      .1       0   410.2    .045       0   425.2      .1       0
Bank Sta=410.2,425.2
XS Rating Curve= 0 ,0
Exp/Cntr=0.3,0.1

Type RM Length L Ch R = 1 ,8198.9  ,391.8,399.9,407.6
XS GIS Cut Line= 3
      1878914.43      393927.435       1879317.8      393855.747
     1879723.334      393792.869
#Sta/Elev= 30
       0 1190.59      60 1173.77    99.9 1161.99   109.9 1158.64   119.9 1153.92
   129.9  1147.5   139.9 1139.96   259.8 1045.51   289.8  1022.5   299.8  1015.5
   309.8 1011.06   319.8 1009.68   399.7 1005.31   402.2 1005.46   409.7  1005.9
   417.2 1007.02   449.7 1012.25   469.8 1017.14   479.8 1020.16   489.8 1024.08
   499.8 1028.76   549.8 1055.18   579.8  1068.9   609.9 1081.61     720 1124.62
     740 1134.12     750 1139.57     760 1145.74     800 1174.82   820.1 1188.61
#Mann= 3 , 0 , 0
       0      .1       0   402.2    .045       0   417.2      .1       0
Bank Sta=402.2,417.2
XS Rating Curve= 0 ,0
Exp/Cntr=0.3,0.1

Type RM Length L Ch R = 1 ,7798.9  ,395.4,399.9,404.5
XS GIS Cut Line= 3
     1878889.926      394177.096     1879292.518      394251.996
      1879695.11      394326.896
#Sta/Elev= 30
       0 1188.73      20 1178.81    79.9 1146.01    89.9 1139.73   189.8 1071.26
   239.7 1037.66   259.7 1025.91   289.6 1010.58   299.6 1005.82   309.6  1001.9
   319.6  999.43   349.6  996.59     402  992.85   409.5  992.51     417  993.01
   429.5  995.49   439.5  998.96   449.4 1003.48   459.4 1009.37   469.4 1016.25
   489.4 1031.16   539.3 1070.88   589.3 1108.64   619.2 1130.67   659.2 1158.82
   689.2 1181.52   749.1 1227.97     779 1250.45     809 1271.95     819 1278.56
#Mann= 3 , 0 , 0
       0      .1       0     402    .045       0     417      .1       0
Bank Sta=402,417
XS Rating Curve= 0 ,0
Exp/Cntr=0.3,0.1

Type RM Length L Ch R = 1 ,7398.9  ,387.2,400,409.8
XS GIS Cut Line= 3
       1878829.9      394488.178     1879209.485      394641.821
     1879589.069      394795.463
#Sta/Elev= 30
       0 1107.63      30  1101.4    59.9 1094.04    69.9 1091.06    89.9 1083.41
   109.9  1073.1   149.8 1049.81   159.8 1044.65   239.7    1008   249.7 1004.25
   269.7  999.71   289.6  996.97   349.6  992.89   369.6  990.77   379.5  988.67
   399.5  982.39     402  982.13   409.5  981.34     417  982.62   419.5  983.05
   429.5  986.82   439.5  991.37   449.4  996.76   519.4 1041.15   629.2 1112.35
   689.2 1146.86     779 1201.91     789 1207.62     809 1217.82     819 1224.66
#Mann= 3 , 0 , 0
       0      .1       0     402    .045       0     417      .1       0
Bank Sta=402,417
XS Rating Curve= 0 ,0
Exp/Cntr=0.3,0.1

Type RM Length L Ch R = 1 ,6998.9  ,400.3,390.3,383.3
XS GIS Cut Line= 3
     1878739.793      394625.144     1878983.033      394966.416
     1879261.288      395264.546
#Sta/Elev= 30
       0 1197.25    49.9  1153.3    69.8 1136.84    99.8 1116.33   179.6 1065.09
   239.5 1019.31   259.4 1005.94   269.4 1000.08   289.4   990.1   299.4  986.62
   309.3  984.56   339.3  981.65   379.2  979.12   389.2  977.46   411.6  971.49
   419.1  970.76   426.6  971.68     429  971.97     439  975.64   448.9   979.9
   458.9  982.82   468.8  984.09   568.3  989.13     628  989.99   687.6  988.34
   717.5  990.82   737.4  994.04   757.3  998.21   787.1 1006.53   826.9 1019.04
#Mann= 3 , 0 , 0
       0      .1       0   411.6    .045       0   426.6      .1       0
Bank Sta=411.6,426.6
XS Rating Curve= 0 ,0
Exp/Cntr=0.3,0.1

Type RM Length L Ch R = 1 ,6608.6  ,420.2,409.6,399.5
XS GIS Cut Line= 2
      1878297.06       394932.79     1878931.846      395291.744
#Sta/Elev= 30
       0 1207.31      20 1195.38      30 1189.84      50 1178.04    69.9 1166.02
    79.9 1160.68    99.9 1150.52   149.8 1122.92   169.8 1112.58   179.8 1107.02
   189.8 1100.81   229.8 1074.36   269.7 1047.29   329.7 1005.61   349.6  991.42
   359.6  983.63   369.6   974.7   379.6  966.67   389.6  963.61     392  963.71
     407  964.64   559.4  976.44   579.4  978.59   589.4  980.64   599.4  984.26
   609.4  989.37   619.4  994.79   649.3 1011.83   669.3 1022.77   729.2 1052.96
#Mann= 3 , 0 , 0
       0      .1       0     392    .045       0     407     .06       0
Bank Sta=392,407
XS Rating Curve= 0 ,0
Exp/Cntr=0.3,0.1

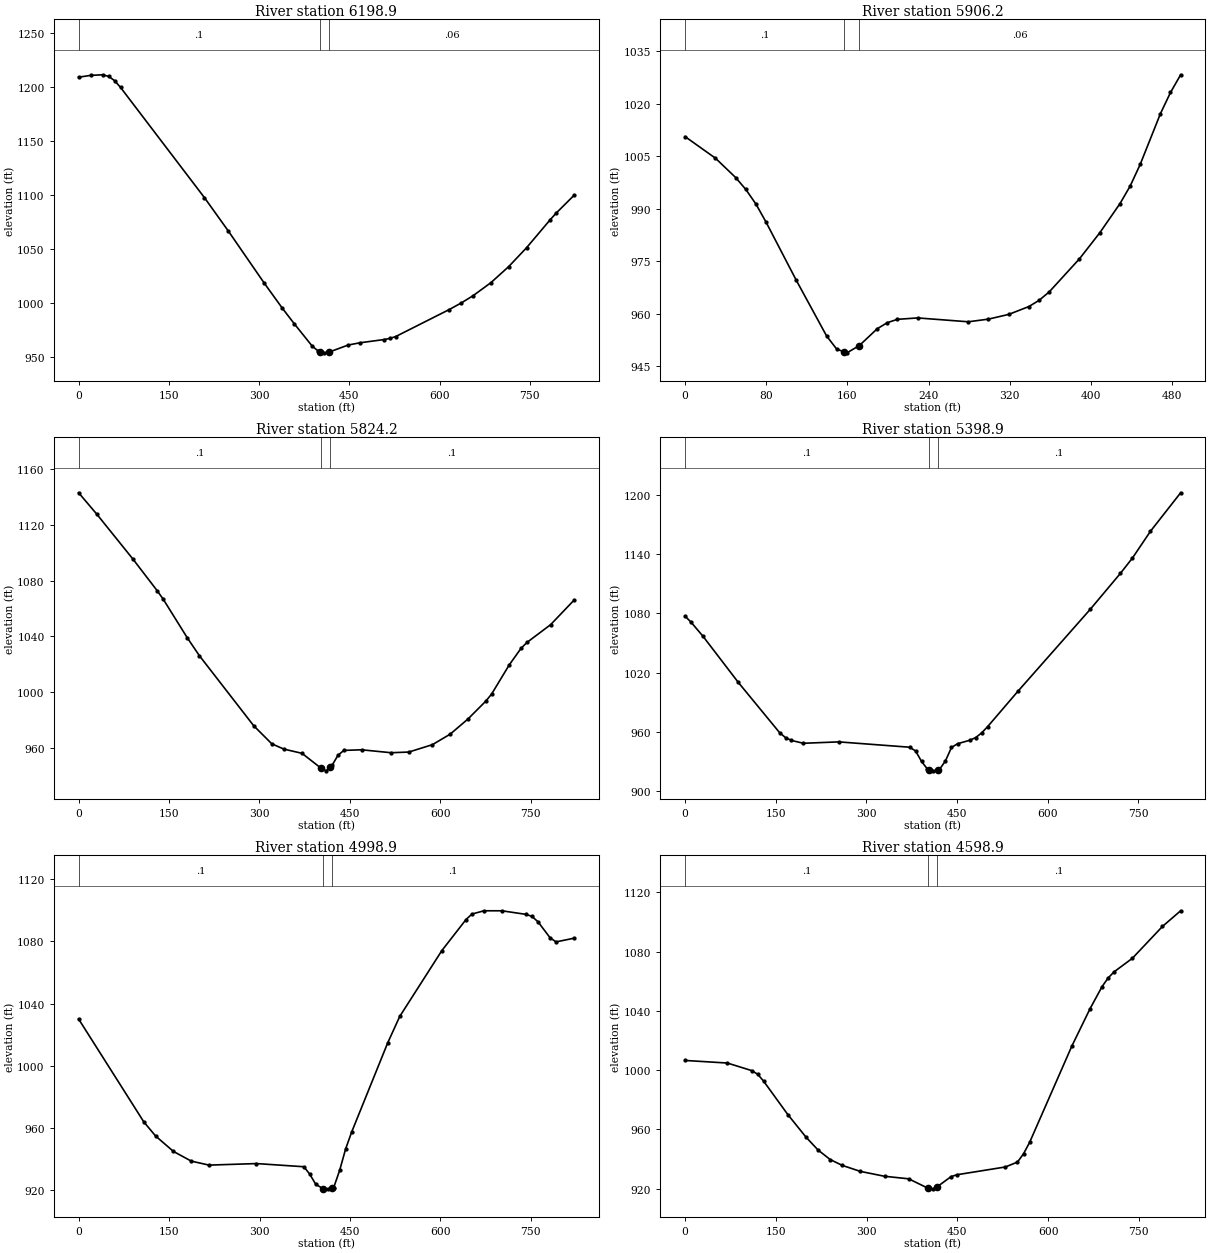
Type RM Length L Ch R = 1 ,6198.9  ,292.6,292.7,292.4
XS GIS Cut Line= 3
     1878135.418      395505.296     1878543.435      395524.273
     1878957.902      395552.217
#Sta/Elev= 30
       0 1209.11    19.9 1210.78    39.8 1211.34    49.8 1209.87    59.8  1205.9
    69.7 1199.63   209.2  1097.7   249.1 1066.67   308.8  1018.5   338.7  995.44
   358.6  981.02   388.5   960.3   398.5  955.79     401  955.39   408.5  954.18
     416  954.78     448  961.37   467.8  963.49   507.4  966.43   517.2  967.47
   527.2  969.26   616.2  994.22   635.9 1000.23   655.7 1006.97   685.4 1019.05
   715.1 1033.97   744.7 1051.36   784.3 1077.46   794.2 1083.54   823.9 1099.98
#Mann= 3 , 0 , 0
       0      .1       0     401    .045       0     416     .06       0
Bank Sta=401,416
XS Rating Curve= 0 ,0
Exp/Cntr=0.3,0.1

Type RM Length L Ch R = 1 ,5906.2  ,87.2,82,77
XS GIS Cut Line= 2
     1878372.382      395807.069      1878860.12      395832.449
#Sta/Elev= 30
       0 1010.59    29.9 1004.43    49.8  998.91    59.8  995.52    69.8  991.34
    79.7  986.22   109.6  969.55   139.5  953.64   149.5  949.88   156.7  949.13
   159.5  948.84   171.7  950.91   189.4  955.73   199.4  957.47   209.3  958.41
   229.2  958.81   279.1  957.71     299  958.47     319  959.82   338.9  962.07
   348.9  963.84   358.8  966.22   388.7   975.7   408.7  983.12   428.6  991.45
   438.6  996.44   448.5 1002.63   468.5 1017.16   478.4 1023.19   488.4 1028.25
#Mann= 3 , 0 , 0
       0      .1       0   156.7    .045       0   171.7     .06       0
Bank Sta=156.7,171.7
XS Rating Curve= 0 ,0
Exp/Cntr=0.3,0.1

Type RM Length L Ch R = 1 ,5824.2  ,410,425.2,440.3
XS GIS Cut Line= 3
     1878132.318       395969.11     1878536.575      395897.491
      1878942.16      395827.969
#Sta/Elev= 30
       0 1143.16      30 1127.86    90.1 1095.49   130.2 1072.84   140.2 1066.76
   180.2 1038.95   200.3 1026.09   290.4  975.74   320.4  962.76   340.5  958.94
   370.5  955.92   402.7  945.04   410.6  943.33   417.7  946.18   420.4  947.26
   430.2  954.51   439.9  958.02   469.3  958.46   518.3  956.35   547.7  956.83
   586.9  962.15   616.3  969.68   645.7  980.53   675.1  993.28   684.9  998.41
   714.3 1019.46   733.9 1031.39   743.7 1035.61   782.9 1048.37     822 1066.09
#Mann= 3 , 0 , 0
       0      .1       0   402.7    .045       0   417.7      .1       0
Bank Sta=402.7,417.7
XS Rating Curve= 0 ,0
Exp/Cntr=0.3,0.1

Type RM Length L Ch R = 1 ,5398.9  ,399.4,400,402.3
XS GIS Cut Line= 3
     1878118.035      396113.619     1878479.838      396308.489
     1878839.505      396503.737
#Sta/Elev= 30
       0  1077.2     9.8  1071.1    29.4 1057.01    88.1 1010.12   156.6  959.18
   166.3  954.25   176.1  951.43   195.7  948.56   254.4  949.97   371.8  944.56
   381.6  940.72   391.4  930.14   401.2  922.37   403.4  921.99     411  920.67
   418.4  921.67   420.9  922.01   430.9  930.68   440.9  944.33   450.9  948.08
   470.8  951.56   480.8  954.26   490.8  959.01   500.8  965.44   550.7 1001.06
   670.5 1084.05   720.4  1120.4   740.3  1135.9   770.3 1163.13   820.2 1202.03
#Mann= 3 , 0 , 0
       0      .1       0   403.4    .045       0   418.4      .1       0
Bank Sta=403.4,418.4
XS Rating Curve= 0 ,0
Exp/Cntr=0.3,0.1

Type RM Length L Ch R = 1 ,4998.9  ,398.6,400,400
XS GIS Cut Line= 3
     1877909.234      396441.158     1878268.051      396645.592
     1878605.273      396876.829
#Sta/Elev= 30
       0    1030   108.2  963.72   127.8  954.63   157.3  944.75   186.8  938.52
   216.3  935.95     295  936.94   373.6   934.9   383.5  930.02   393.3  923.56
   405.5  920.78     413  920.67   420.5  921.15   422.9   921.3   432.9  932.53
   442.9  946.45   452.9   957.3   512.7 1014.73   532.6  1031.7   602.4 1074.07
   642.4 1094.02   652.3  1097.6   672.3 1099.72   702.2 1099.71   742.1  1097.4
     752 1096.08     762 1092.58     782  1082.3   791.9 1079.69   821.9 1082.08
#Mann= 3 , 0 , 0
       0      .1       0   405.5    .045       0   420.5      .1       0
Bank Sta=405.5,420.5
XS Rating Curve= 0 ,0
Exp/Cntr=0.3,0.1

Type RM Length L Ch R = 1 ,4598.9  ,398.6,400,401.3
XS GIS Cut Line= 3
     1877687.244      396739.224     1878029.688      396963.942
     1878367.637      397195.171
#Sta/Elev= 30
       0 1006.56    69.9 1004.81   109.9  999.73   119.9  997.29   129.9  992.52
   169.8  970.01   199.8   954.8   219.8  946.07   239.8  939.66   259.7  935.71
   289.7  931.65   329.7  928.35   369.6  926.64   402.1  920.16   409.6  919.87
   417.1  921.38   439.6  928.12   449.5   929.4   529.4  934.63   549.4  937.94
   559.4  943.54   569.4  951.17   639.3 1016.29   669.3 1041.45   689.2 1056.41
   699.2 1062.23   709.2 1066.43   739.2  1075.5   789.1 1097.07   819.1 1107.62
#Mann= 3 , 0 , 0
       0      .1       0   402.1    .045       0   417.1      .1       0
Bank Sta=402.1,417.1
XS Rating Curve= 0 ,0
Exp/Cntr=0.3,0.1

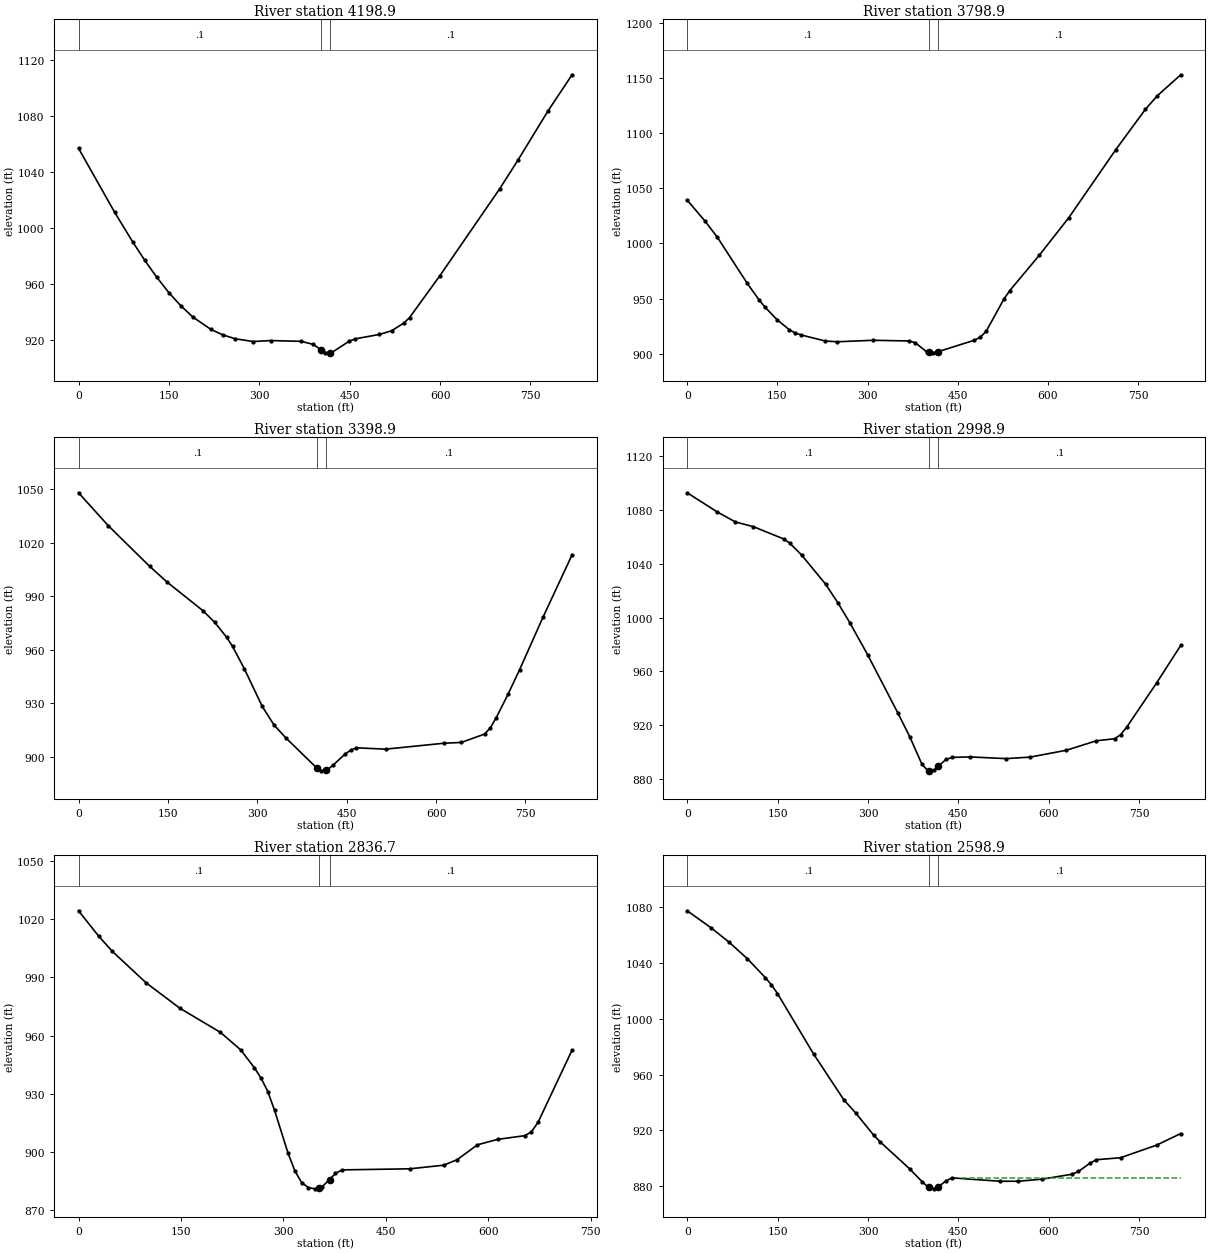
Type RM Length L Ch R = 1 ,4198.9  ,393.2,400,404.1
XS GIS Cut Line= 3
     1877447.494      397025.724     1877775.089       397271.42
     1878099.689       397521.13
#Sta/Elev= 30
       0 1056.78    59.9 1011.15    89.9  989.98   109.9  976.86   129.8  964.75
   149.8  953.86   169.8  944.34   189.8  936.34   219.7  927.51   239.7   923.6
   259.7  920.88   289.6  918.89   319.6  919.56   369.5  919.01   389.5  916.85
     402  913.14   409.5  910.99     417  910.86   419.5  910.81   449.4  919.18
   459.4   920.8   499.4  923.96   519.4  926.53   539.4  931.94   549.3  935.95
   599.3  965.65   699.2 1028.07   729.1 1048.27   779.1 1083.48     819 1109.27
#Mann= 3 , 0 , 0
       0      .1       0     402    .045       0     417      .1       0
Bank Sta=402,417
XS Rating Curve= 0 ,0
Exp/Cntr=0.3,0.1

Type RM Length L Ch R = 1 ,3798.9  ,402,399.8,401.4
XS GIS Cut Line= 3
     1877249.072      397219.091     1877489.665      397549.905
     1877764.493      397856.902
#Sta/Elev= 30
       0 1039.19    29.9    1020    49.9 1005.78    99.8  963.88   119.7  948.72
   129.7   942.1   149.6  930.83   169.6  921.91   179.6   918.9   189.6  917.05
   229.5  911.63   249.4  910.89   309.3  912.25   369.1  911.62   379.1  910.14
   399.1   901.5   401.6  901.34     409  900.87   416.6  901.79   477.7  912.27
   487.5  914.98   497.4  920.41   526.8   949.5   536.6  957.23   585.6  989.16
   634.7 1023.18   713.2 1085.05   762.2 1121.38   781.8 1133.58   821.1 1152.74
#Mann= 3 , 0 , 0
       0      .1       0   401.6    .045       0   416.6      .1       0
Bank Sta=401.6,416.6
XS Rating Curve= 0 ,0
Exp/Cntr=0.3,0.1

Type RM Length L Ch R = 1 ,3398.9  ,409.1,400,389.2
XS GIS Cut Line= 3
     1876895.487      397461.816     1877167.524       397765.24
     1877426.801      398096.593
#Sta/Elev= 30
       0 1048.15    49.7 1029.75   119.3 1006.84   149.1  997.85   208.7  981.95
   228.6  975.35   248.5  967.01   258.4  961.91   278.3  949.28   308.1  928.27
     328  917.76   347.9  910.46     400  893.51   407.5  891.97     415  892.38
   417.3   892.5   427.1  895.16   446.7  901.21   456.4  903.52   466.2  904.91
   515.2  904.15     613  907.47   642.4  907.92   681.5  912.63   691.3  916.26
     701  921.85   720.6  934.88   740.2  948.79   779.3  978.16   828.2 1013.27
#Mann= 3 , 0 , 0
       0      .1       0     400    .045       0     415      .1       0
Bank Sta=400,415
XS Rating Curve= 0 ,0
Exp/Cntr=0.3,0.1

Type RM Length L Ch R = 1 ,2998.9  ,161.8,162.3,162.8
XS GIS Cut Line= 3
     1876577.723      397925.338     1876949.482       398097.06
     1877321.843      398267.463
#Sta/Elev= 30
       0 1092.47    49.9 1078.25    79.9 1070.85   109.9 1067.35   159.8 1058.29
   169.8  1055.3   189.8 1046.37   229.7 1024.68   249.7 1011.13   269.7  996.28
   299.6  972.27   349.6  929.18   369.6  911.36   389.5  891.22   399.5  886.34
     402  886.48   409.5  886.88     417  889.94   429.5  894.77   439.5  896.29
   469.4  896.66   529.4   895.4   569.3  896.53   629.2   901.6   679.2  908.65
   709.1  910.11   719.1  913.09   729.1  918.53     779  951.53     819  979.33
#Mann= 3 , 0 , 0
       0      .1       0     402    .045       0     417      .1       0
Bank Sta=402,417
XS Rating Curve= 0 ,0
Exp/Cntr=0.3,0.1

Type RM Length L Ch R = 1 ,2836.7  ,229.1,237.7,246.4
XS GIS Cut Line= 2
     1876548.332      398082.442     1877198.281      398398.037
#Sta/Elev= 30
       0  1024.4    29.7 1011.22    49.5 1003.46      99   987.2   148.5  974.08
   207.8  961.64   237.5   952.6   257.3  943.46   267.2  938.04   277.1  931.14
     287  921.38   306.8  899.23   316.7  890.19   326.6  884.14   336.5  881.57
   346.4  880.91   352.6  881.55   356.3  881.93   367.6   885.7   376.1  888.85
     386  890.69     485  891.25   534.5   893.1   554.3  895.95     584  903.64
   613.6  906.44   653.2  908.34   663.1  910.31     673  915.45   722.5   952.5
#Mann= 3 , 0 , 0
       0      .1       0   352.6    .045       0   367.6      .1       0
Bank Sta=352.6,367.6
XS Rating Curve= 0 ,0
Exp/Cntr=0.3,0.1

Type RM Length L Ch R = 1 ,2598.9  ,253.8,252,250.1
XS GIS Cut Line= 3
     1876441.692      398114.495      1876716.43      398418.154
     1876991.168      398721.814
#Sta/Elev= 30
       0 1077.51      40 1065.16    69.9 1054.83    99.9 1043.06   129.8 1029.48
   139.8 1024.35   149.8 1018.14   209.7  974.78   259.7  942.02   279.7  932.38
   309.6  916.42   319.6  911.96   369.6  892.16   389.5  883.26   399.5  879.37
     402  879.03   409.5     878     417  879.58   429.5  883.73   439.5  885.86
   519.4  883.44   549.3  883.44   589.3  884.97   639.2  888.54   649.2  890.45
   669.2  896.66   679.2   898.9   719.1  900.32     779  909.37     819  917.67
#Mann= 3 , 0 , 0
       0      .1       0     402    .045       0     417      .1       0
#XS Ineff= 2 , 0
                          453.59          885.82
Permanent Ineff=
       F       F
Bank Sta=402,417
XS Rating Curve= 0 ,0
Exp/Cntr=0.3,0.1