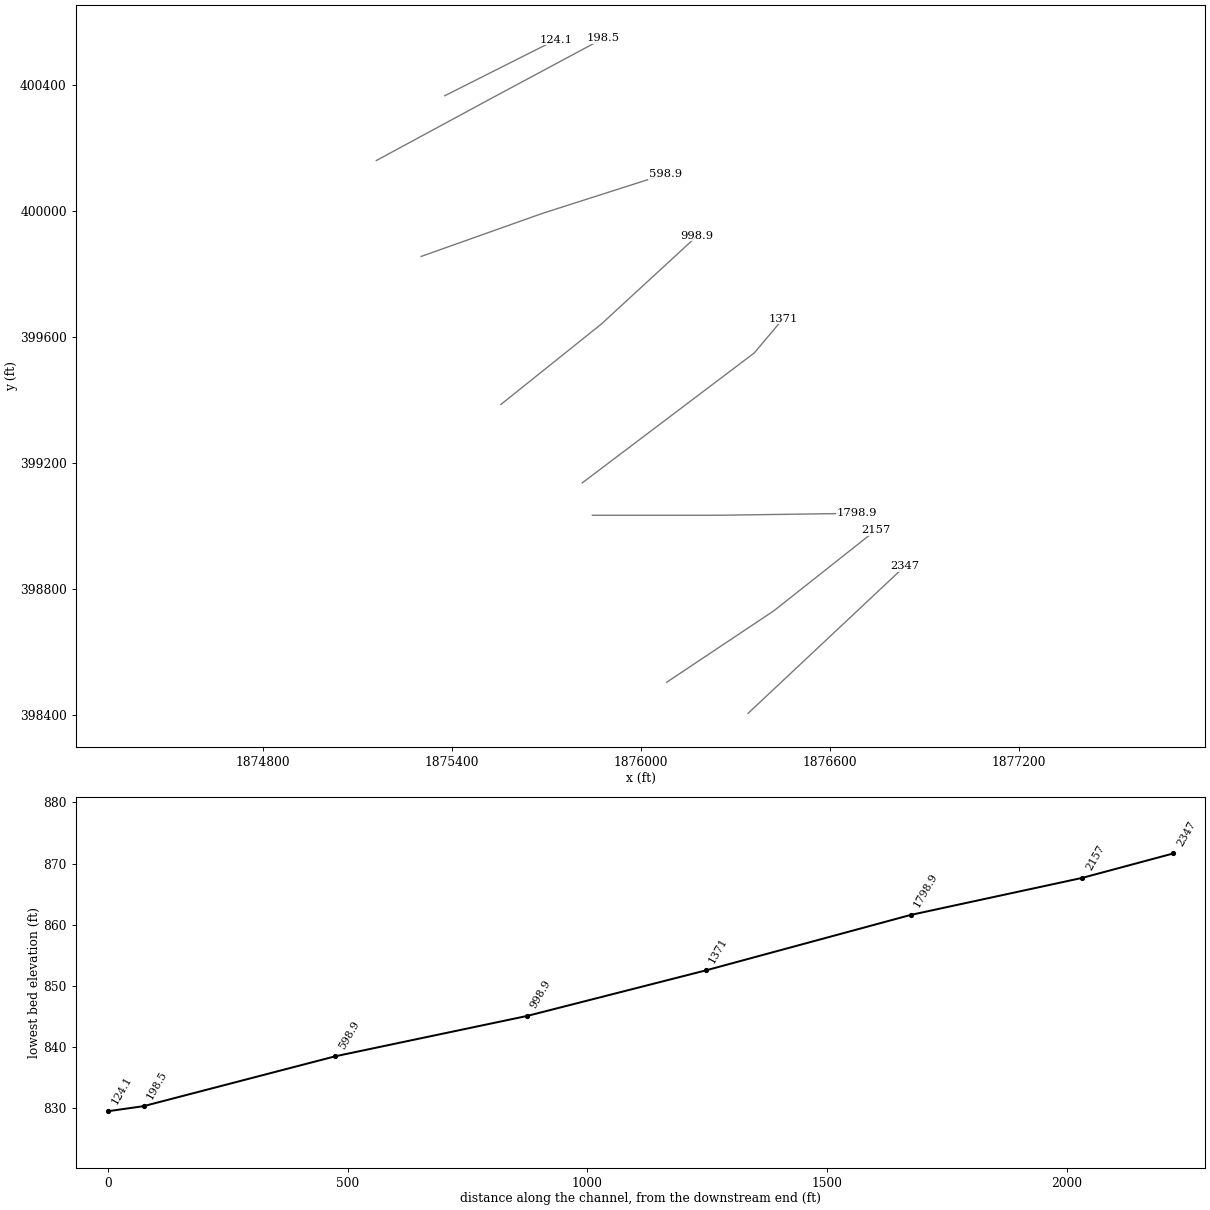
HEC-RAS study PowlltnFrk.prj: PowlltnFrk

--- PowlltnFrk.g01 (geometry) --- (continued)

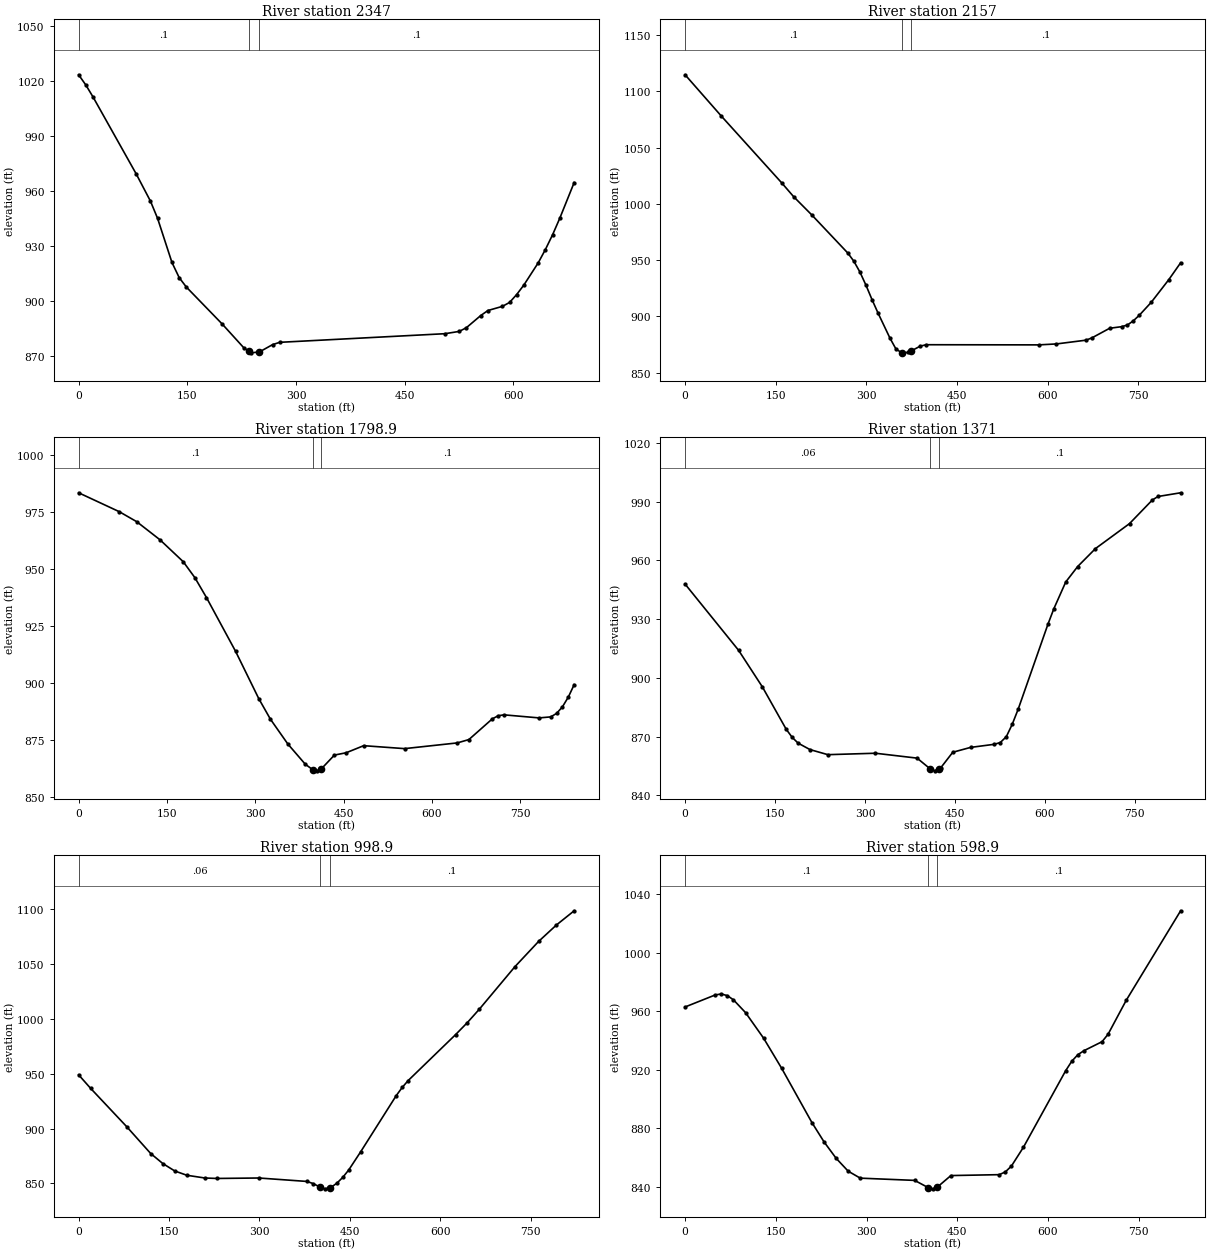
Type RM Length L Ch R = 1 ,2347    ,193.7,190,186.3
XS GIS Cut Line= 2
     1876339.774      398404.658     1876838.547      398872.533
#Sta/Elev= 30
       0 1023.19     9.9 1017.64    19.8 1011.15    79.3  969.28    99.1  954.35
     109   944.9   128.8   920.9   138.8  912.63   148.7  907.49   198.2  887.34
     228  874.39   234.5   872.6   237.9  871.66   249.5  872.15   267.6  876.12
   277.5  877.39   505.5  882.09   525.3  883.34   535.2  885.38     555     892
   564.9  894.73   584.8  896.98   594.7  899.11   604.6  903.45   614.5  908.63
   634.3  920.72   644.2  927.97   654.1     936     664  944.97   683.9  964.48
#Mann= 3 , 0 , 0
       0      .1       0   234.5    .045       0   249.5      .1       0
Bank Sta=234.5,249.5
XS Rating Curve= 0 ,0
Exp/Cntr=0.3,0.1

Type RM Length L Ch R = 1 ,2157    ,371.3,358.1,345.1
XS GIS Cut Line= 3
     1876081.466      398503.455     1876421.936      398730.435
     1876744.579      398985.414
#Sta/Elev= 30
       0 1114.69    59.9 1078.06   159.7 1018.81   179.6 1006.45   209.6  990.26
   269.5  956.25   279.4  949.04   289.4  939.48   299.4  927.81   309.4  915.03
   319.4  903.02   339.3  880.57   349.3  870.86   359.2  867.66   369.3  867.99
   374.2  869.31   389.2  873.59   399.2  874.87   585.4  874.73   614.8  875.57
   663.8  878.92   673.6  880.98   702.9  889.49   722.5  890.89   732.3  892.38
   742.1  896.12   751.9  901.02   771.5   912.4   800.8  932.69   820.4  947.67
#Mann= 3 , 0 , 0
       0      .1       0   359.2    .045       0   374.2      .1       0
Bank Sta=359.2,374.2
XS Rating Curve= 0 ,0
Exp/Cntr=0.3,0.1

Type RM Length L Ch R = 1 ,1798.9  ,413.3,428,442.4
XS GIS Cut Line= 3
     1875845.358      399033.665     1876250.023      399033.665
     1876686.876      399039.843
#Sta/Elev= 30
       0   983.5    69.1   975.2    98.7  970.82   138.2  962.88   177.7  953.27
   197.4  946.29   217.1  937.57   266.5  914.02     306  893.22   325.7  884.24
   355.3  873.36   384.9   864.5   397.2  862.16   404.7  861.59   412.2  862.45
   434.4   868.5   454.3  869.51   484.1  872.62   553.6  871.33     643  873.83
   662.8   875.3   702.6  884.38   712.5  885.74   722.4  886.14     782   884.8
   801.8  885.24   811.8  886.78   821.7  889.67   831.6   893.9   841.6  899.38
#Mann= 3 , 0 , 0
       0      .1       0   397.2    .045       0   412.2      .1       0
Bank Sta=397.2,412.2
XS Rating Curve= 0 ,0
Exp/Cntr=0.3,0.1

Type RM Length L Ch R = 1 ,1371    ,371.3,372,374.2
XS GIS Cut Line= 3
     1875813.376      399136.568     1876359.637      399548.965
     1876451.051      399657.608
#Sta/Elev= 30
       0  947.87    89.3  914.02     129  895.31   168.6  873.74   178.6  869.59
   188.5  866.64   208.3  863.35   238.1  860.76   317.4  861.49   386.9  858.99
   408.3  853.61   416.6   852.5   423.3   853.6   426.5  854.12   446.4  861.99
   476.1  864.47   515.8  866.06   525.7  866.97   535.7  869.95   545.6   876.3
   555.5  884.01   605.1  927.36     615  935.32   634.8  948.96   654.7  956.85
   684.4  966.02   741.2  978.78   779.1  990.79   788.6  992.61   826.4  994.51
#Mann= 3 , 0 , 0
       0     .06       0   408.3    .045       0   423.3      .1       0
Bank Sta=408.3,423.3
XS Rating Curve= 0 ,0
Exp/Cntr=0.3,0.1

Type RM Length L Ch R = 1 ,998.9   ,407.5,400,390.2
XS GIS Cut Line= 3
     1875554.539      399385.237     1875873.763      399640.618
     1876178.018      399920.529
#Sta/Elev= 30
       0  948.98    19.9  936.67    79.8   901.7   119.6  877.24   139.6  868.15
   159.5  861.34   179.5  857.44   209.4  854.94   229.3  854.52   299.1  854.94
   378.9   851.8   388.9  849.89   401.3  846.48   408.8  845.06   416.3  846.05
   418.6  846.36   428.5  850.23   438.3  855.54   448.2  862.31   467.9  878.78
   526.9  929.98   536.8  937.44   546.6  943.67   625.4  985.61     645  996.62
   664.7 1008.72   723.8 1047.51   763.2  1070.6   792.7 1085.55   822.2 1098.53
#Mann= 3 , 0 , 0
       0     .06       0   401.3    .045       0   416.3      .1       0
Bank Sta=401.3,416.3
XS Rating Curve= 0 ,0
Exp/Cntr=0.3,0.1

Type RM Length L Ch R = 1 ,598.9   ,396.9,400.4,404.5
XS GIS Cut Line= 3
     1875301.484      399855.384     1875687.366      399992.309
     1876077.688      400116.991
#Sta/Elev= 30
       0  962.87    49.9  971.11    59.9  971.76    69.9  970.62    79.9  967.77
    99.9  959.02   129.8   941.5   159.8  920.79   209.7  883.76   229.7  870.58
   249.7  859.35   269.6  850.54   289.6  845.77   379.5  844.24     402  839.27
   409.5  838.46     417  839.66   439.4  847.54   519.4  848.16   529.4  850.04
   539.4     854   559.4  866.97   629.3  919.38   639.3  925.77   649.3  930.23
   659.3  932.95   689.3  939.12   699.3  944.26   729.3  967.48   819.2 1028.67
#Mann= 3 , 0 , 0
       0      .1       0     402    .045       0     417      .1       0
Bank Sta=402,417
XS Rating Curve= 0 ,0
Exp/Cntr=0.3,0.1

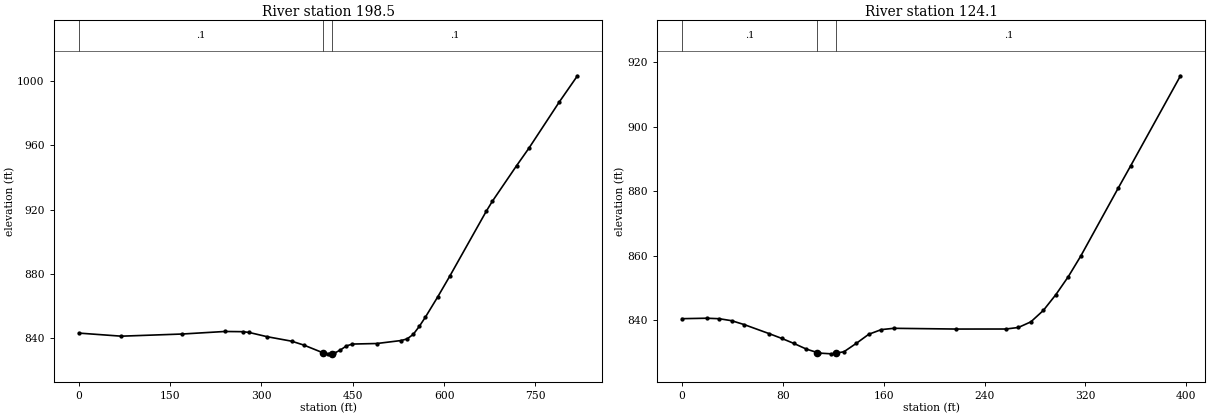
Type RM Length L Ch R = 1 ,198.5   ,75,74.3,73.7
XS GIS Cut Line= 3
     1875158.902      400159.761     1875519.186       400354.41
     1875880.152      400547.784
#Sta/Elev= 30
       0   843.2    69.9  841.28   169.8  842.62   239.7   844.2   269.7  844.07
   279.7   843.6   309.6  840.93   349.6  838.16   369.6  835.74   400.5  831.03
   409.5  830.29   415.5   830.5   419.5  830.64   429.5  832.65   439.5   835.2
   449.4  836.38   489.4  836.71   529.4  838.57   539.3  839.59   549.3  842.41
   559.3   847.4   569.3  853.15   589.3  865.58   609.3  878.62   669.2  918.98
   679.2  925.19   719.1  947.39   739.1  958.14     789  986.91     819 1003.29
#Mann= 3 , 0 , 0
       0      .1       0   400.5    .045       0   415.5      .1       0
Bank Sta=400.5,415.5
XS Rating Curve= 0 ,0
Exp/Cntr=0.3,0.1

Type RM Length L Ch R = 1 ,124.1   ,123.2,124.1,125.1
XS GIS Cut Line= 2
     1875376.437       400365.54      1875729.55        400543.2
#Sta/Elev= 29
       0  840.38    19.8  840.52    29.6  840.37    39.5  839.75    49.4  838.55
    69.2  835.74    79.1  834.27    88.9  832.68    98.8  830.92   107.5  829.85
   108.7   829.7   118.6  829.46   122.5  829.71   128.5   830.1   138.4  832.74
   148.2  835.54   158.1  836.98     168  837.39   217.4  837.16   256.9  837.17
   266.8  837.65   276.7   839.4   286.6  842.95   296.5  847.84   306.4  853.45
   316.2  859.79   345.9  880.91   355.8  887.84   395.3  915.82
#Mann= 3 , 0 , 0
       0      .1       0   107.5    .045       0   122.5      .1       0
Bank Sta=107.5,122.5
XS Rating Curve= 0 ,0
Exp/Cntr=0.3,0.1

Chan Stop Cuts=-1
Use User Specified Reach Order=0
Composite Channel Slope=5